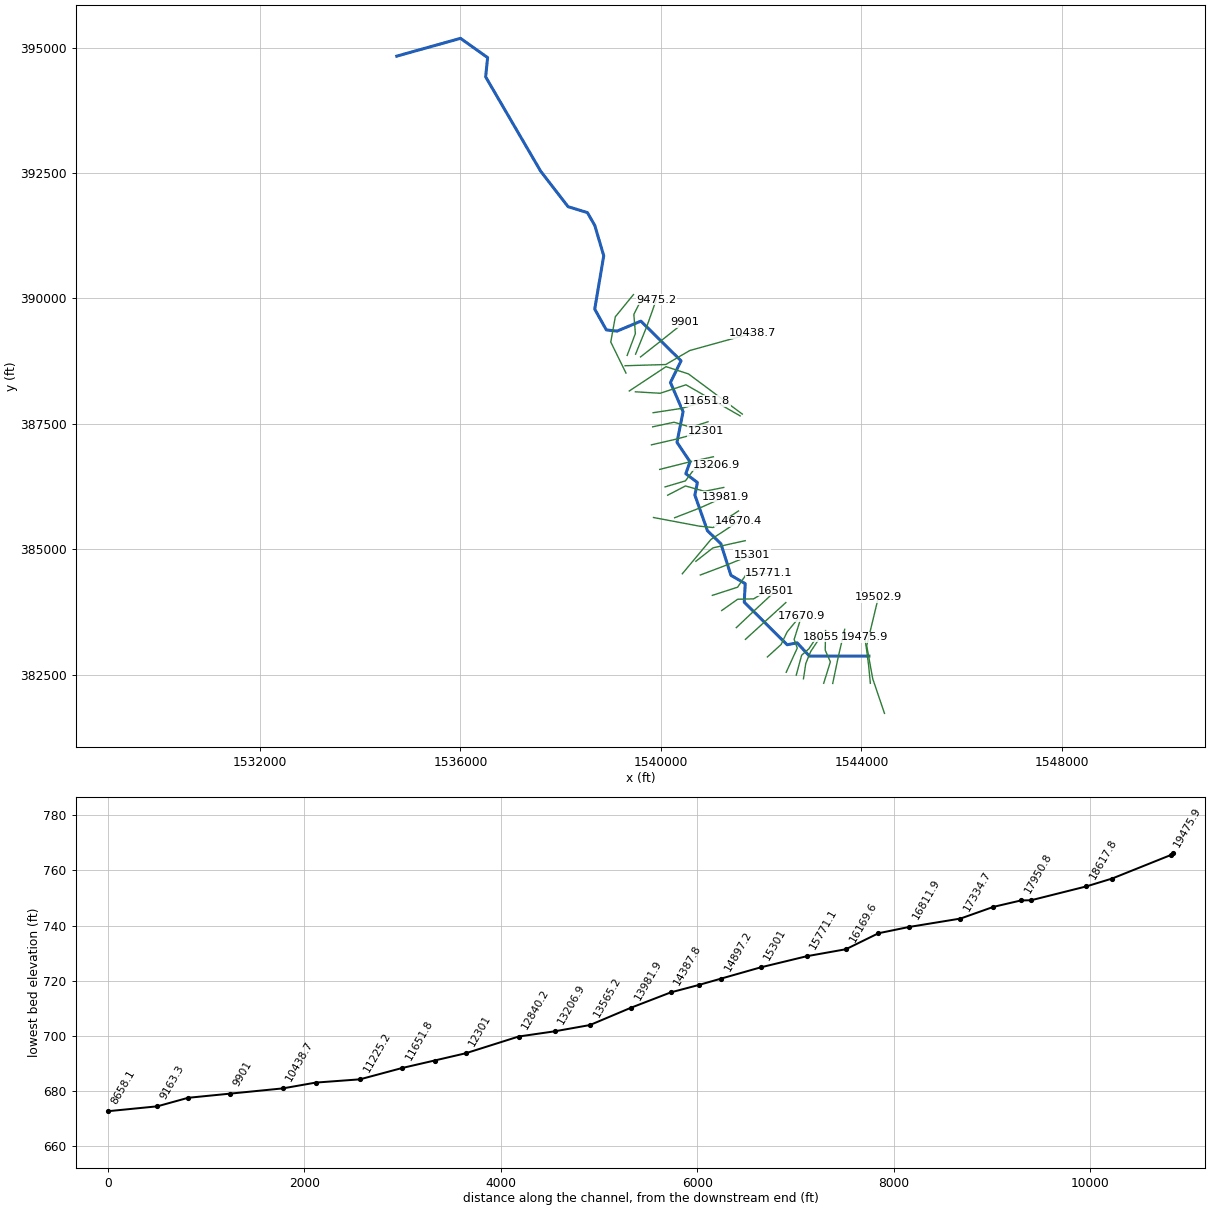
--- RFMILLCR.prj (project) ---

Proj Title=RFMILLCR
Current Plan=p01
Default Exp/Contr=0,0
English Units
Geom File=g01
Flow File=f01
Plan File=p01
BEGIN DESCRIPTION:
END DESCRIPTION:
DSS Export Rating Curves= 0
DSS Export Rating Curve Sorted= 0
DSS Export Volume Flow Curves= 0
DXF OffsetX= 0
DXF OffsetY= 0
DXF ScaleX= 0
DXF ScaleY= 0

--- RFMILLCR.p01 (plan) ---

Plan Title=Floodplain
Program Version=4.00
Geom File=g01
Flow File=f01
K Sum by GR=0
Std Step Tol=0.01
Critical Tol=0.01
Num of Std Step Trials=20
Max Error Tol=0.3
Flow Tol Ratio=0.001
Split Flow NTrial=30
Split Flow Tol=0.02
Split Flow Ratio=0.02
Log Output Level=0
Friction Slope Method=1
Unsteady Friction Slope Method=2
Unsteady Bridges Friction Slope Method=1
Global Log Level=0
CheckData=False
Run HTab=0
Run UNet=0
Run PostProcess=0
UNET Theta=0
UNET Theta Warmup=0
UNET ZTol=0
UNET ZSATol=0
UNET MxIter=0
UNET MaxInSteps=0
UNET DtIC=0
UNET DtMin=0
UNET MaxCRTS=0
UNET WFStab=0
UNET SFStab=0
UNET WFX=0
UNET SFX=0
UNET DSS MLevel=0
UNET DZMax Abort=0
UNET Convert EG Bridges=0
UNET Use Existing IB Tables=0
UNET Froude Limit=0
UNET Froude Power=0
Write IC File=0
Echo Input=False
Echo Output=False
Write Detailed=0

--- RFMILLCR.f01 (steady flow) ---

Flow Title=NFF Regression Equation
Program Version=4.00
Number of Profiles= 1
Profile Names=P100yr
River Rch & RM=RFMILLCR,Main            ,19502.9
     317
River Rch & RM=RFMILLCR,Main            ,19475.9
     368
River Rch & RM=RFMILLCR,Main            ,18879.1
     374
River Rch & RM=RFMILLCR,Main            ,17670.9
     415
River Rch & RM=RFMILLCR,Main            ,16169.6
     452
River Rch & RM=RFMILLCR,Main            ,14670.4
     501
River Rch & RM=RFMILLCR,Main            ,14387.8
     633
River Rch & RM=RFMILLCR,Main            ,10774.4
     670
River Rch & RM=RFMILLCR,Main            ,10438.7
    1028
River Rch & RM=RFMILLCR,Main            ,8658.1
    1075
River Rch & RM=RFMILLCR,Main            ,8368.5
    1258
River Rch & RM=RFMILLCR,Main            ,6264
    1282
River Rch & RM=RFMILLCR,Main            ,5655.1
    1424
River Rch & RM=RFMILLCR,Main            ,2438.5
    1483
River Rch & RM=RFMILLCR,Main            ,1741.1
    1654
River Rch & RM=RFMILLCR,Main            ,263.1
    1679
Boundary for River Rch & Prof#=RFMILLCR,Main            , 1
Up Type= 0
Dn Type= 3
Dn Slope=0.004921
DSS Import GetInterval= 0
DSS Import GetPeak= 0
DSS Import FillOption= 0

--- RFMILLCR.g01 (geometry) ---

Geom Title=USGS 10m DEM
Program Version=4.00

River Reach=RFMILLCR        ,Main
Reach XY= 30
      1544148.84      382873.487     1542961.861      382872.912
     1542715.751      383138.258     1542516.735      383099.004
      1541660.82      383948.898     1541680.659      384316.902
     1541394.865      384484.176     1541195.111      385112.966
     1540927.291      385370.801     1540676.157      386081.922
     1540726.196      386333.384     1540495.012      386508.584
      1540579.68      386745.876     1540319.075      387133.092
      1540440.83      387744.337     1540188.568      388325.687
     1540400.615      388758.007     1539599.082      389549.041
     1539125.007      389350.312     1538909.945      389373.372
     1538678.116      389787.798      1538858.01      390851.347
     1538678.712      391457.606     1538532.498      391711.372
     1538146.729      391829.622     1537601.168      392534.476
       1536502.2      394416.826     1536541.621      394800.751
     1536001.027      395184.517     1534728.436      394829.503

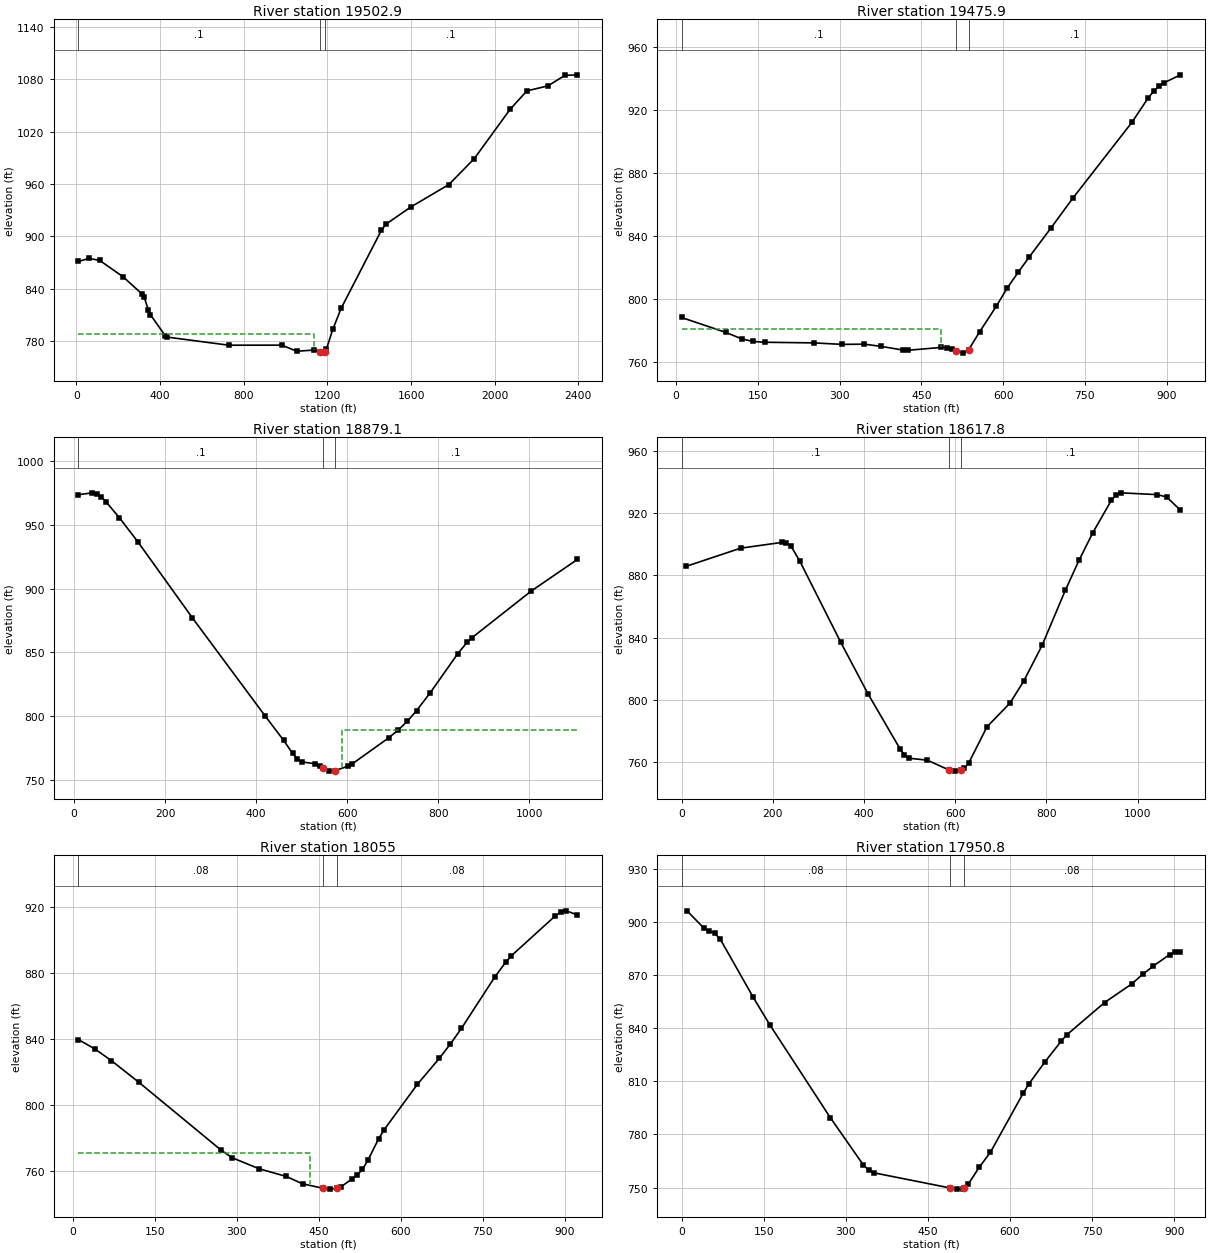
Type RM Length L Ch R = 1 ,19502.9 ,26.7,27,27.4
XS GIS Cut Line= 4
     1544458.486      381731.898     1544223.959      382422.078
     1544104.332      383080.414     1544337.872      384050.366
#Sta/Elev= 30
    10.1  871.26    60.7  874.75   111.4  872.43   222.7   853.8   313.8  834.04
     324  830.66   344.2   815.5   354.3  810.19   425.2  786.04   435.3  784.55
   728.9  775.28   982.4  775.37  1053.4  768.35  1134.5  769.71  1162.5  767.36
    1175  766.21  1187.5  767.69  1195.3  770.66  1225.7  793.31  1266.3  817.73
  1458.5     907  1478.7  913.75  1599.6  933.75    1781  959.39  1901.9  988.92
  2073.2  1045.4  2153.9 1066.72  2254.6 1072.45  2335.3 1084.44  2395.7 1085.12
#Mann= 3 , 0 , 0
    10.1      .1       0  1162.5    .045       0  1187.5      .1       0
#XS Ineff= 2 , 0
         1134.04  787.61
Permanent Ineff=
       F       F
Bank Sta=1162.5,1187.5
XS Rating Curve= 0 ,0
Exp/Cntr=0.3,0.1

Type RM Length L Ch R = 1 ,19475.9 ,612.6,596.7,588.7
XS GIS Cut Line= 4
     1544176.565      382331.177     1544142.433      382684.905
     1544102.096      382995.193     1544064.861       383249.63
#Sta/Elev= 30
    10.2  788.27    91.4  778.78   121.8  774.54   142.1  773.02   162.5  772.53
   253.8  772.12   304.6  771.17   345.2  771.32   375.6  769.95   415.9   767.6
     426  767.45   486.6  769.24   496.7  769.08   506.8  768.05   514.5  766.75
     527  765.62   537.1   767.9   557.2  779.26   587.5  795.35   607.7  807.01
   627.9  817.06   648.1  826.77   688.1  845.23   727.6  863.91   836.4  912.29
   866.1  927.72     876  931.95   885.9  935.19   895.7  937.46   925.4  942.46
#Mann= 3 , 0 , 0
    10.2      .1       0   514.5    .045       0   537.1      .1       0
#XS Ineff= 2 , 0
          485.31   780.7
Permanent Ineff=
       F       F
Bank Sta=514.5,537.1
XS Rating Curve= 0 ,0
Exp/Cntr=0.3,0.1

Type RM Length L Ch R = 1 ,18879.1 ,242,261.3,280.2
XS GIS Cut Line= 3
     1543425.667      382328.074     1543540.441      382876.455
      1543665.11      383407.135
#Sta/Elev= 30
      10  973.49      40  974.99      50  974.24      60  971.96      70  968.16
     100  955.38   140.1  936.76   260.1  877.07   420.2  800.07   460.2  781.25
   480.2   770.9   490.2  766.62   500.2  764.32   530.2   762.8   540.3   761.2
   547.8  759.36   560.3  757.08   572.8  757.45   600.6  760.83   610.7  762.68
   691.5  783.26   711.7   789.2   731.9  796.12   752.1  804.41   782.4  818.53
   842.9  849.15   863.1  857.91   873.2  861.35  1004.4   898.2  1105.4  922.85
#Mann= 3 , 0 , 0
      10      .1       0   547.8    .045       0   572.8      .1       0
#XS Ineff= 2 , 0
                          587.82          789.43
Permanent Ineff=
       F       F
Bank Sta=547.8,572.8
XS Rating Curve= 0 ,0
Exp/Cntr=0.3,0.1

Type RM Length L Ch R = 1 ,18617.8 ,484.2,562.8,424.1
XS GIS Cut Line= 4
       1543245.7      382331.177     1543379.124      382759.374
     1543276.729      382988.988     1543282.935      383383.054
#Sta/Elev= 30
      10  885.78   129.6  897.47   219.3  901.15   229.2  900.99   239.2  899.18
   259.1  889.31   348.8   837.2   408.6  804.05   478.7  768.72   488.7  764.64
   498.8  762.51     539  761.28   586.8   754.9   599.3  754.23   611.8  755.04
   619.5  756.11   629.5  759.31   669.7  782.67   720.1  797.91   750.4  812.07
   790.9  835.22   841.4  870.32   871.7  889.76     902  907.51   942.4  928.18
   952.6  931.68   962.7  933.03  1043.5  931.87  1063.7  930.35    1094  921.88
#Mann= 3 , 0 , 0
       0      .1       0   586.8    .045       0   611.8      .1       0
Bank Sta=586.8,611.8
XS Rating Curve= 0 ,0
Exp/Cntr=0.3,0.1

Type RM Length L Ch R = 1 ,18055   ,117.3,104.2,91
XS GIS Cut Line= 4
     1542842.325       382421.16     1542888.869      382728.346
     1542988.161      382967.267     1543183.643      383262.041
#Sta/Elev= 30
      10  839.64    40.1  833.92    70.2  826.92   120.3  813.85   270.6  772.87
   290.6  768.27   340.5   761.5   390.3  756.86   420.2  752.37   457.4  749.74
   469.9  749.19   482.4  749.63   489.8   750.5   509.7  755.11   519.7  757.54
   529.6  761.08   539.6  766.61   559.5   779.8   569.4  785.14   630.1  812.55
   670.5  828.36   690.7  837.01   710.9  846.45   771.5  877.32   791.8  886.41
   801.9  890.25   882.7  914.51   892.8  916.82   902.9  917.52   923.1     915
#Mann= 3 , 0 , 0
      10     .08       0   457.4    .045       0   482.4     .08       0
#XS Ineff= 2 , 0
          432.93  771.05
Permanent Ineff=
       F       F
Bank Sta=457.4,482.4
XS Rating Curve= 0 ,0
Exp/Cntr=0.3,0.1

Type RM Length L Ch R = 1 ,17950.8 ,245.5,279.9,313.7
XS GIS Cut Line= 4
     1542697.896      382492.913     1542805.762      382891.186
     1542949.583      383018.412     1543121.061      383272.864
#Sta/Elev= 30
    10.1  906.44    40.3  896.85    50.3  894.95    60.4  893.79    70.4  890.62
   130.8  857.65     161  842.15   271.7  789.57   332.1   762.8   342.2  759.69
   352.2  758.29   491.1  749.74   503.6  749.11   513.7  749.43   516.1  750.01
   523.8  751.89     544  761.53   564.2  769.88   624.4  803.45   634.3  808.46
     664   821.1   693.7  832.78   703.6  836.27   772.9  854.61   822.4  865.09
   842.2  870.47     862  875.25   891.7  881.73   901.6  883.24   911.5  883.41
#Mann= 3 , 0 , 0
       0     .08       0   491.1    .045       0   516.1     .08       0
Bank Sta=491.1,516.1
XS Rating Curve= 0 ,0
Exp/Cntr=0.3,0.1

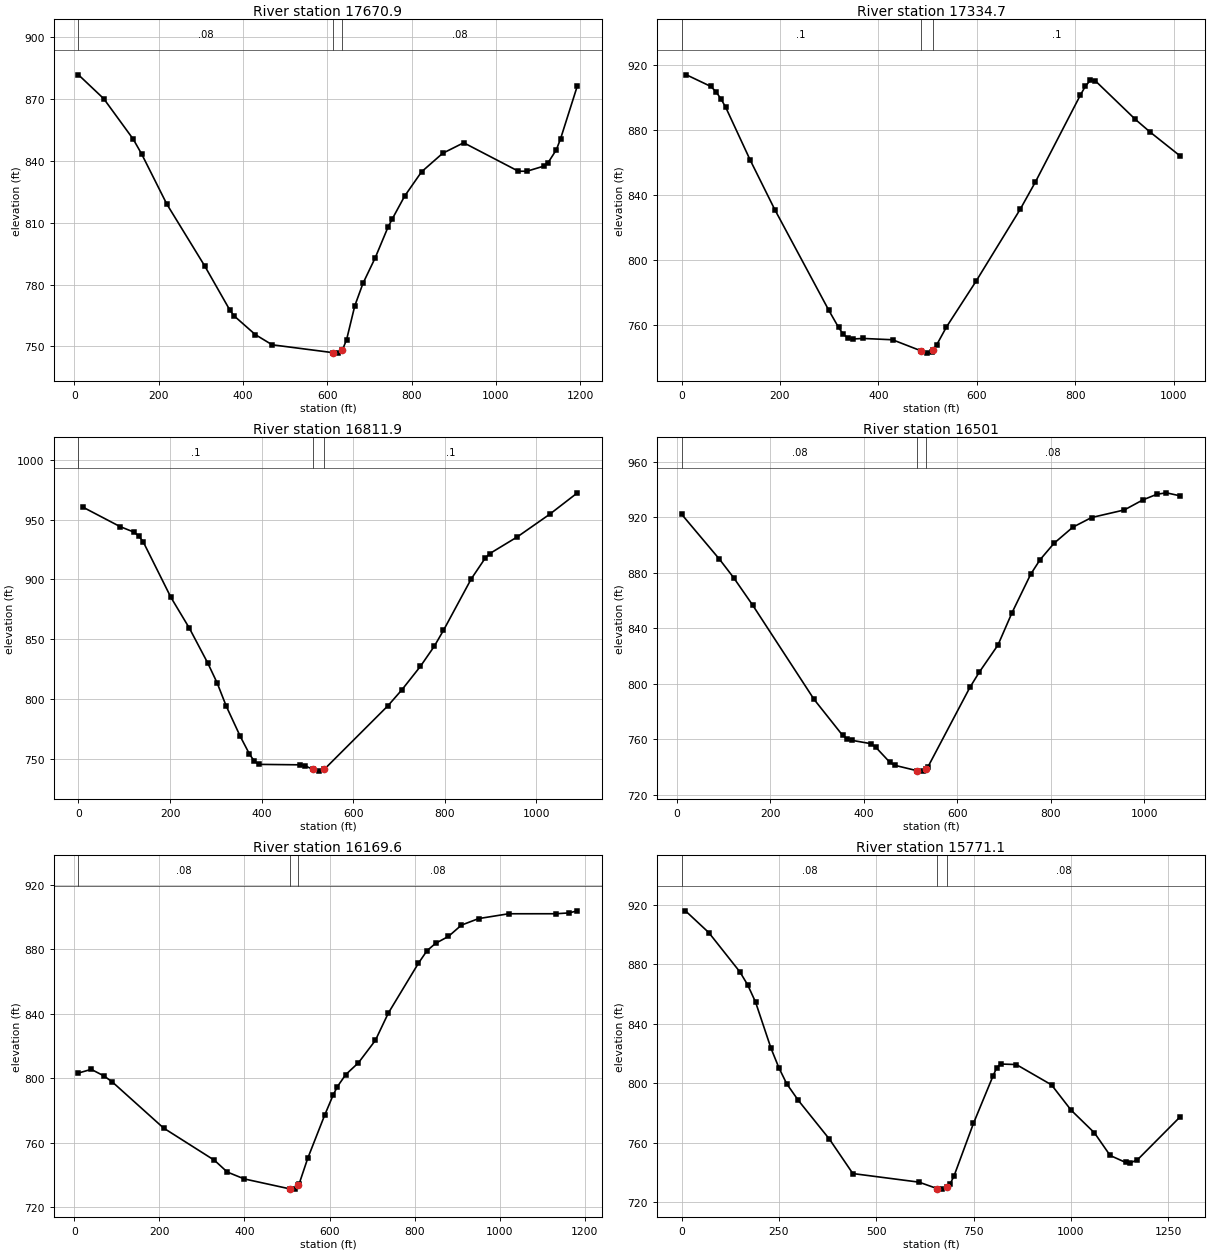
Type RM Length L Ch R = 1 ,17670.9 ,359.5,336.2,312.9
XS GIS Cut Line= 4
     1542498.057      382551.283      1542718.21      383032.428
     1542656.153      383206.189     1542801.186      383663.165
#Sta/Elev= 30
      10  881.73    69.9  870.15   139.8  850.53   159.7  843.36   219.6  818.98
   309.5  788.98   369.4  767.47   379.4  764.76   429.3  755.76   469.2  750.82
   613.7     747   626.2  746.78   635.9  748.37   645.7  753.29   665.1  769.68
   684.5  780.58   713.6  793.01   743.6  807.71   753.6   811.7   783.5  822.96
   823.5   834.7   873.4  843.66   923.4  848.79  1053.2  834.98  1073.2  834.98
  1113.2  837.45  1123.2  839.03  1143.1   845.4  1153.1  850.73  1193.1  876.51
#Mann= 3 , 0 , 0
      10     .08       0   613.7    .045       0   635.9     .08       0
Bank Sta=613.7,635.9
XS Rating Curve= 0 ,0
Exp/Cntr=0.3,0.1

Type RM Length L Ch R = 1 ,17334.7 ,534.3,522.9,519.9
XS GIS Cut Line= 4
     1542122.457      382855.564      1542395.51      383103.794
     1542516.523      383355.128     1542749.239       383637.49
#Sta/Elev= 30
      10  913.73    59.8  906.55    69.8  903.37    79.8  899.12    89.8  893.75
   139.6  861.26   189.5  830.84   299.2  768.92   319.2   758.3   329.1  753.99
   339.1  751.67   349.1  751.23     369  751.55   428.8  750.74     486  744.01
   498.5  742.52   508.5  743.43     511  744.47   518.5  747.61   538.4  758.62
   598.2   786.6   688.6  831.21   719.1   847.8   810.6  901.31   820.8  906.79
   830.9   910.4   841.1  909.97   922.4  886.27   952.9  878.35  1013.9  863.66
#Mann= 3 , 0 , 0
       0      .1       0     486    .045       0     511      .1       0
Bank Sta=486,511
XS Rating Curve= 0 ,0
Exp/Cntr=0.3,0.1

Type RM Length L Ch R = 1 ,16811.9 ,310.3,310.9,311.3
XS GIS Cut Line= 2
     1541684.563      383207.353     1542491.312      383940.409
#Sta/Elev= 30
    10.1  960.37    90.8  944.19   121.1  939.57   131.2  936.47   141.3   931.5
   201.9  884.94   242.2  859.18   282.6  829.82   302.8  813.42     323  793.72
   353.3  768.67   373.4  753.84   383.5  748.12   393.6  745.13   484.5  744.74
   494.6  744.05   512.3  740.87   524.8  739.47   537.3  741.08   676.2  794.25
   706.5  807.52   746.9  827.11   777.2  843.93   797.4   857.3   857.9  900.29
   888.2  917.55   898.3  921.53   958.8  935.59  1029.5  954.52  1090.1  972.45
#Mann= 3 , 0 , 0
       0      .1       0   512.3    .045       0   537.3      .1       0
Bank Sta=512.3,537.3
XS Rating Curve= 0 ,0
Exp/Cntr=0.3,0.1

Type RM Length L Ch R = 1 ,16501   ,352.3,331.4,310.5
XS GIS Cut Line= 3
     1541502.268      383440.069     1541885.436      383801.897
     1542289.219      384176.613
#Sta/Elev= 30
    10.1  922.23    91.2  889.82   121.6  876.51   162.2   856.8   293.9  788.79
   354.7  763.02   364.9  760.38     375  759.35   415.5  756.95   425.7  754.42
   456.1  743.49   466.2  741.41   514.5  737.46     527  737.19  533.59  739.07
     537  739.93   627.2  797.44   647.2  808.38   687.3  827.97   717.3  851.19
   757.4  878.98   777.4   889.4   807.4  901.28   847.5  912.82   887.6  919.79
   957.7  925.25   997.7  932.53  1027.8  936.59  1047.8  937.58  1077.9  935.35
#Mann= 3 , 0 , 0
    10.1     .08       0   514.5    .045       0  533.59     .08       0
Bank Sta=514.5,533.59
XS Rating Curve= 0 ,0
Exp/Cntr=0.3,0.1

Type RM Length L Ch R = 1 ,16169.6 ,371.8,398.5,425.2
XS GIS Cut Line= 4
     1541211.373      383781.386     1541529.419      384006.345
     1541847.464      384014.102     1542254.717      384258.454
#Sta/Elev= 30
      10  803.32      40  805.58    69.9  801.51    89.9  797.68   209.8  769.26
   329.6  749.23   359.6  741.98   399.5  737.71   506.3  731.56   518.8  731.38
  526.15  733.91   528.7  734.73   548.6  750.37   588.4  777.11   608.3  789.56
   618.2  794.81   638.1  802.35   667.9  809.66   707.7  823.54     738  840.38
   808.8  871.29     829  879.09   849.2  883.66   879.5  887.97   909.8  894.93
   950.2  898.99    1021  901.99  1132.1     902  1162.4  902.51  1182.6  903.81
#Mann= 3 , 0 , 0
      10     .08       0   506.3    .045       0  526.15     .08       0
Bank Sta=506.3,526.15
XS Rating Curve= 0 ,0
Exp/Cntr=0.3,0.1

Type RM Length L Ch R = 1 ,15771.1 ,487.3,470.1,453.7
XS GIS Cut Line= 4
       1541025.2      384083.917     1541529.419      384246.819
     1541684.563      384479.535     1542153.874      384526.078
#Sta/Elev= 30
      10  915.85      70  901.23     150  874.78     170  866.02     190   854.6
   229.9   823.4   249.9  810.48   269.9  799.73   299.9  788.48   379.9  762.39
   439.9   739.3   609.8  733.53   657.2  729.13   669.7  728.84   682.2  730.43
   689.7  732.33   699.7  737.65   749.6     773   799.6  804.71   809.6  810.57
   819.6   812.9   859.7  812.56   950.1   798.9  1000.2  781.96  1060.4  766.62
  1100.6  751.46  1140.7  746.75  1150.7  746.29  1170.8  748.56  1281.2  777.63
#Mann= 3 , 0 , 0
       0     .08       0   657.2    .045       0   682.2     .08       0
Bank Sta=657.2,682.2
XS Rating Curve= 0 ,0
Exp/Cntr=0.3,0.1

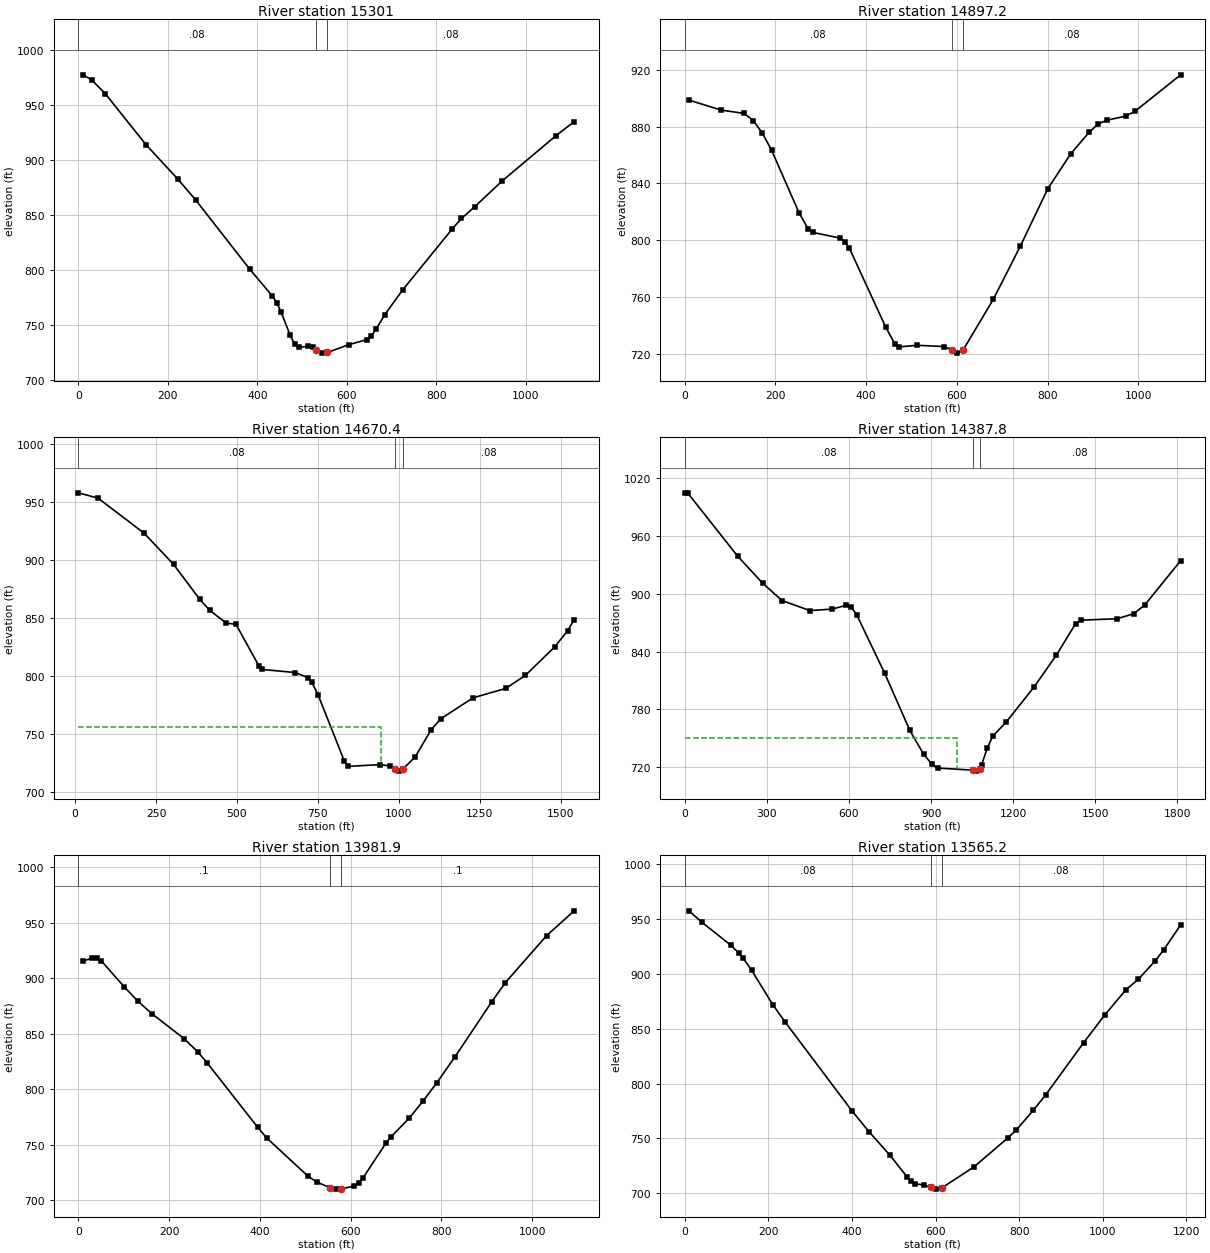
Type RM Length L Ch R = 1 ,15301   ,407.6,403.8,399.2
XS GIS Cut Line= 3
     1540784.761      384489.936      1541293.96      384681.585
     1541816.435      384894.545
#Sta/Elev= 30
    10.1   977.5    30.2  972.82    60.5  960.23   151.1  914.14   221.7  883.07
     262  864.02   382.9  801.15   433.2  776.81   443.3  770.72   453.4  761.99
   473.5  740.92   483.6  732.95   493.7   730.1   513.8  730.99   523.9  730.15
   531.6  727.85   544.1  724.78   556.6  725.39   604.5  732.49   644.8  737.01
   654.9  740.32     665  746.24   685.1   759.8   725.4   782.4   836.3  837.81
   856.4  847.08   886.6   857.9   947.1  881.03    1068  922.34  1108.3     935
#Mann= 3 , 0 , 0
       0     .08       0   531.6    .045       0   556.6     .08       0
Bank Sta=531.6,556.6
XS Rating Curve= 0 ,0
Exp/Cntr=0.3,0.1

Type RM Length L Ch R = 1 ,14897.2 ,217,226.8,236.7
XS GIS Cut Line= 4
     1540695.519      384762.673     1541036.479      385030.164
     1541335.202      385097.617     1541680.684      385173.804
#Sta/Elev= 30
    10.1  898.56    80.6   891.6     131   889.3   151.2  884.17   171.3  875.29
   191.5  863.29     252  819.37   272.1  807.99   282.2  805.59   342.7  801.59
   352.7  799.05   362.8   794.6   443.2  738.87     463  727.27   472.9  725.06
   512.4  726.19   571.7  725.31   588.8  722.77   601.3  720.68   613.8  722.94
   680.3  758.51   739.6  795.73   800.3  836.21   850.8  860.77   891.2  875.88
   911.4  881.86   931.7  884.58   972.1  887.41   992.3  890.68  1093.4  916.44
#Mann= 3 , 0 , 0
       0     .08       0   588.8    .045       0   613.8     .08       0
Bank Sta=588.8,613.8
XS Rating Curve= 0 ,0
Exp/Cntr=0.3,0.1

Type RM Length L Ch R = 1 ,14670.4 ,287.5,282.6,277.7
XS GIS Cut Line= 4
     1540425.471      384513.957     1540997.935      385198.797
     1541246.281      385359.977     1541539.057       385556.61
#Sta/Elev= 30
    10.1  957.61      71  953.05     213  922.98   304.3  896.05   385.4  865.96
   415.9  856.59   466.6  845.71     497   844.5     568  808.73   578.2  805.76
   679.6  803.13   720.2  798.61   730.3  795.15   750.6  783.87   831.7  726.91
   841.9  722.42   941.9  723.96   971.5  722.86   988.6  720.03  1001.1  718.37
  1013.6  720.47  1050.5  730.65  1099.8  754.01  1129.4  763.33    1229   781.4
  1329.7  789.42  1390.2  800.58  1480.9  825.07  1521.2  839.05  1541.3  848.59
#Mann= 3 , 0 , 0
    10.1     .08       0   988.6    .045       0  1013.6     .08       0
#XS Ineff= 2 , 0
          944.76   756.1
Permanent Ineff=
       F       F
Bank Sta=988.6,1013.6
XS Rating Curve= 0 ,0
Exp/Cntr=0.3,0.1

Type RM Length L Ch R = 1 ,14387.8 ,391.2,405.9,421.1
XS GIS Cut Line= 4
     1539850.192      385635.186     1540767.633      385462.592
     1541037.921      385435.445     1541546.467      385765.515
#Sta/Elev= 30
       0 1004.94    10.1 1004.94   192.8  939.18   284.1  911.12   355.1  893.01
   456.6  882.58   537.8  884.07   588.5  887.95   608.8  886.09   629.1  877.56
   730.6  817.21   821.9  758.21   872.7  733.14   903.1  722.82   923.4  718.89
  1051.8  716.74  1064.3   715.7  1076.8   718.1  1084.5  722.33  1104.6   739.3
  1124.7  751.82    1175  766.98  1275.9  803.11  1356.8  835.91  1427.5  868.81
  1447.7  872.61  1579.1  874.07  1639.7  879.18  1680.1  888.24  1811.5  934.36
#Mann= 3 , 0 , 0
       0     .08       0  1051.8    .045       0  1076.8     .08       0
#XS Ineff= 2 , 0
          994.17  750.63
Permanent Ineff=
       F       F
Bank Sta=1051.8,1076.8
XS Rating Curve= 0 ,0
Exp/Cntr=0.3,0.1

Type RM Length L Ch R = 1 ,13981.9 ,435.8,416.7,397.3
XS GIS Cut Line= 3
     1540272.166      385630.075     1540781.954      385828.015
     1541279.896      386051.627
#Sta/Elev= 30
    10.1  915.43    30.4  918.35    40.5  918.05    50.6  915.72   101.3  892.21
   131.7   879.2     162  868.15   232.9  845.68   263.3  833.75   283.6  823.96
     395  765.94   415.2  756.18   506.4  721.65   526.6  716.32   554.6  711.29
   567.1  710.11   579.6  710.28   607.5  712.91   617.6  715.43   627.7  720.43
   678.3  751.78   688.4  756.94   728.8  773.84   759.1  789.09   789.5  805.59
   829.9  829.19   910.8  878.64   941.1  896.15  1032.1  938.46  1092.7  960.77
#Mann= 3 , 0 , 0
       0      .1       0   554.6    .045       0   579.6      .1       0
Bank Sta=554.6,579.6
XS Rating Curve= 0 ,0
Exp/Cntr=0.3,0.1

Type RM Length L Ch R = 1 ,13565.2 ,325.6,358.3,388.5
XS GIS Cut Line= 4
     1540133.276      386079.639     1540488.499      386264.176
     1540866.662      386157.515     1541252.057      386234.231
#Sta/Elev= 30
      10  957.48      40  947.34   110.1  926.15   130.1   918.6   140.1   914.1
   160.1   903.2   210.2   872.1   240.2  856.03   400.3  774.96   440.6  756.27
     491   734.6   531.3  715.22   541.3  711.09   551.4  708.61   571.6  707.72
   589.3  705.38   601.8  703.83   614.3  704.77   692.5  724.27   773.1   750.6
   793.2   757.8   833.5  775.54   863.7  789.92   954.4  837.46  1004.8  862.56
  1055.2  885.45  1085.4  895.23  1125.7  912.04  1145.9  921.95  1186.2  944.64
#Mann= 3 , 0 , 0
       0     .08       0   589.3    .045       0   614.3     .08       0
Bank Sta=589.3,614.3
XS Rating Curve= 0 ,0
Exp/Cntr=0.3,0.1

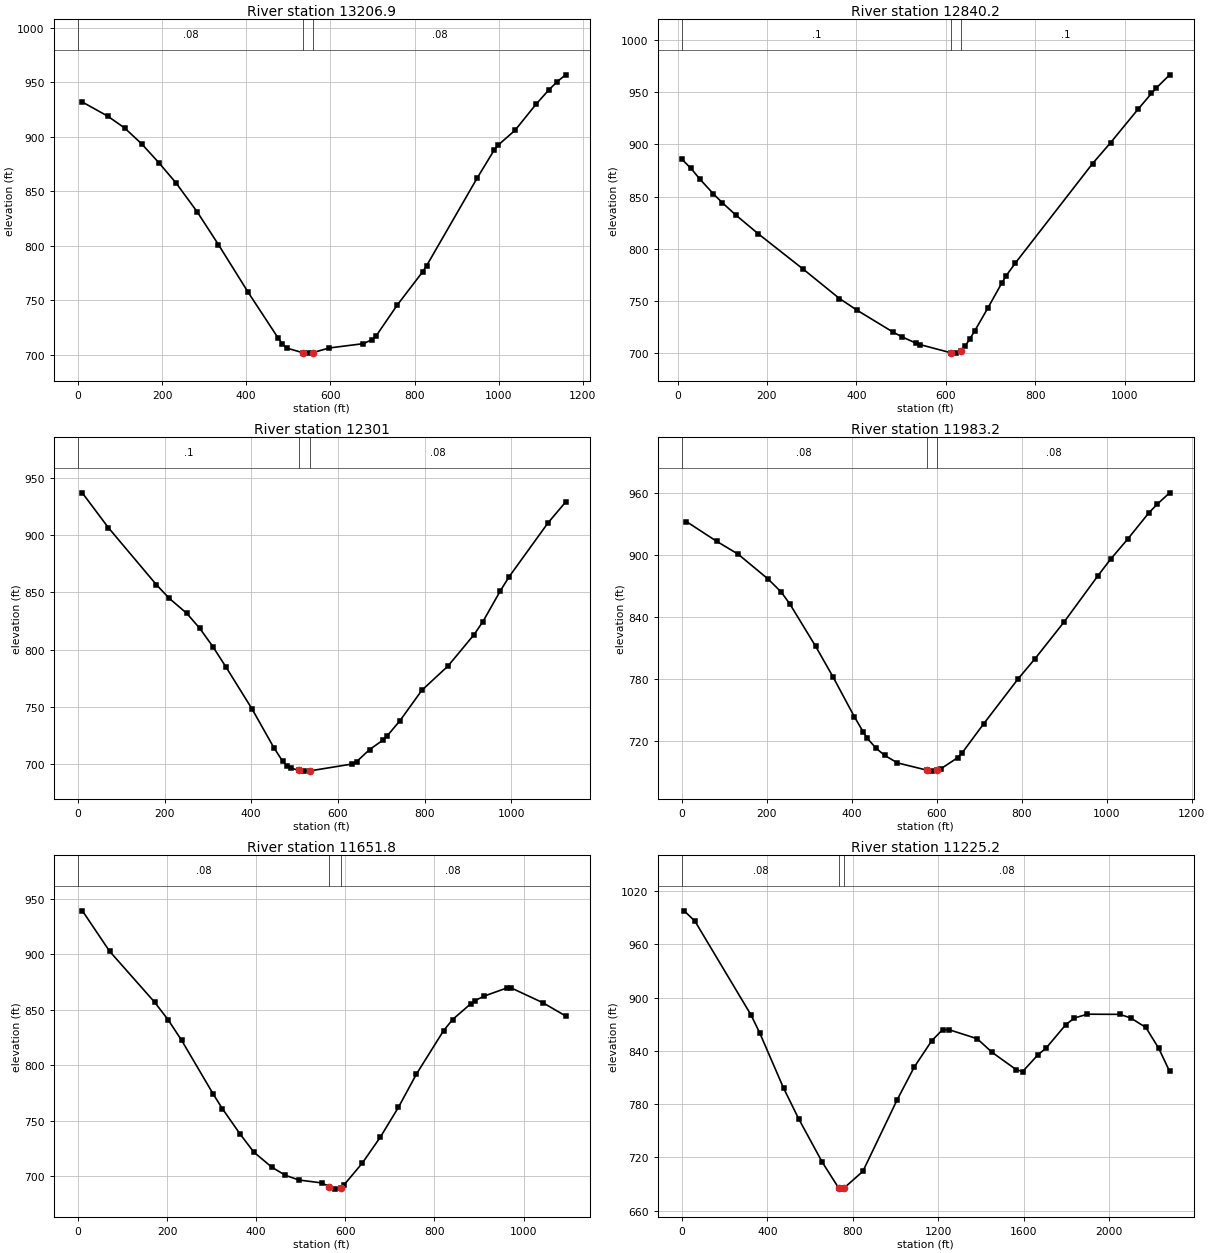
Type RM Length L Ch R = 1 ,13206.9 ,384.9,366.7,350.2
XS GIS Cut Line= 4
     1540081.245      386244.784     1540488.499       386365.99
     1540658.188      386593.858     1541099.379      386681.126
#Sta/Elev= 30
    10.1  932.06    70.8  919.03   111.3  908.05   151.8  893.45   192.2  876.36
   232.7  857.93   283.3   831.3   333.9  801.13   404.7  757.29   475.6  715.52
   485.8  710.11   495.9  706.19   534.2  701.98   546.7  701.55   559.2  702.12
   597.4   706.3   678.6  710.25   698.9  713.89     709  717.52     759  745.76
     819  776.05   828.9  781.96   948.9  862.29   988.9  887.69   998.8  892.49
  1038.8  906.06  1088.8     930  1118.8  942.97  1138.8   950.6  1158.8  956.94
#Mann= 3 , 0 , 0
       0     .08       0   534.2    .045       0   559.2     .08       0
Bank Sta=534.2,559.2
XS Rating Curve= 0 ,0
Exp/Cntr=0.3,0.1

Type RM Length L Ch R = 1 ,12840.2 ,539.3,539.2,541.3
XS GIS Cut Line= 3
     1539974.584      386593.858      1540579.68      386745.875
     1541046.048      386845.967
#Sta/Elev= 30
    10.1  885.65    30.2  876.91    50.3  866.57    80.5  852.42   100.6   843.9
   130.8  832.07   181.1  814.06   281.8  780.06   362.3  752.08   402.5  740.62
     483  719.63   503.1   715.1   533.3  709.26   543.4  707.74   611.4  700.01
   623.9  699.66     634  701.82   644.2  706.87   654.3  713.54   664.5  720.71
   694.9  743.44   725.4   766.9   735.5  774.11   755.8  786.15   928.4  881.58
     969  901.76  1029.8  933.56  1060.3  948.92  1070.4  953.85  1100.9  966.79
#Mann= 3 , 0 , 0
    10.1      .1       0   611.4    .045       0     634      .1       0
Bank Sta=611.4,634
XS Rating Curve= 0 ,0
Exp/Cntr=0.3,0.1

Type RM Length L Ch R = 1 ,12301   ,332.4,317.8,301.9
XS GIS Cut Line= 3
     1539809.743      387083.531     1540318.848      387200.851
       1540900.6      387359.882
#Sta/Elev= 30
      10  937.21    70.3  906.69   180.8   856.9     211  844.77   251.2  831.74
   281.3  818.53   311.5  802.56   341.6  784.79   401.9  747.98   452.1  714.22
   472.2  702.39   482.3  698.38   492.3  696.18   509.9  694.24   522.4  693.57
   534.9  693.76     633   699.8   643.1  701.84   673.2  712.43   703.4  720.55
   713.4  724.23   743.6  737.86   793.8  764.34   854.2  785.59   914.5  813.15
   934.6  824.37   974.8  851.26   994.9  863.55  1085.3  911.04  1125.5  929.06
#Mann= 3 , 0 , 0
       0      .1       0   509.9    .045       0   534.9     .08       0
Bank Sta=509.9,534.9
XS Rating Curve= 0 ,0
Exp/Cntr=0.3,0.1

Type RM Length L Ch R = 1 ,11983.2 ,318.5,331.3,347.4
XS GIS Cut Line= 4
     1539833.985      387442.302     1540260.631      387534.419
     1540600.009      387432.605     1540939.386      387544.115
#Sta/Elev= 30
    10.2  932.52    81.2  913.48     132  900.96     203  876.75   233.5  864.29
   253.8  852.77   314.7  811.67   355.3   782.3     406  743.39   426.3   729.1
   436.5  722.58   456.7   713.1     477   706.2   507.3  698.89   575.8  691.94
   588.3  690.93   600.8  691.58   608.6  693.01   649.1  703.95   659.2  708.46
   709.8  736.51   790.8  780.01   830.5  799.45     900  835.56   979.3   880.1
  1009.1  896.14  1048.8   915.3  1098.4  940.61  1118.3  949.16    1148  960.31
#Mann= 3 , 0 , 0
       0     .08       0   575.8    .045       0   600.8     .08       0
Bank Sta=575.8,600.8
XS Rating Curve= 0 ,0
Exp/Cntr=0.3,0.1

Type RM Length L Ch R = 1 ,11651.8 ,422.7,426.7,427.5
XS GIS Cut Line= 3
     1539843.681      387723.501     1540414.096       387810.28
     1540910.297      387956.217
#Sta/Elev= 30
    10.1  939.28    70.9  902.89   172.1  856.85   202.4  840.98   232.8  822.39
   303.7  773.88   323.9  760.91   364.4  737.61   394.8  721.57   435.3  707.92
   465.6  700.67     496  696.43   546.6  693.83   564.5   690.5     577   688.2
   589.5  689.47   597.3  692.13   637.8  711.51   678.4  734.99     719  761.87
   759.5  791.92   820.4  831.09   840.7   841.2   881.2  855.32   891.4  858.36
   911.6  862.35   962.4  869.67   972.5  869.66  1043.5  856.34  1094.2  844.47
#Mann= 3 , 0 , 0
       0     .08       0   564.5    .045       0   589.5     .08       0
Bank Sta=564.5,589.5
XS Rating Curve= 0 ,0
Exp/Cntr=0.3,0.1

Type RM Length L Ch R = 1 ,11225.2 ,468.1,450.8,433.5
XS GIS Cut Line= 4
     1539489.759       388140.45      1539984.28      388111.361
     1540498.984      388279.919     1541579.356      387660.473
#Sta/Elev= 30
    10.1  997.87    60.7  986.12   323.5  880.23     364  860.03   475.2  798.08
   545.5  763.65   655.9  714.65   733.6  685.21   746.1   684.1   758.6  685.41
   846.4  704.13  1006.9  784.78  1087.6  821.97  1168.6   851.3  1219.2  863.82
  1249.6  863.86  1381.2  853.71  1452.1  838.16  1563.5  818.93  1593.8  816.54
  1664.7   835.2  1705.2   843.4  1796.3  869.53  1836.8  877.07  1897.6  881.33
  2049.5  881.14  2100.1   877.1    2171  866.36  2231.7  842.68  2282.3  816.77
#Mann= 3 , 0 , 0
       0     .08       0   733.6    .045       0   758.6     .08       0
Bank Sta=733.6,758.6
XS Rating Curve= 0 ,0
Exp/Cntr=0.3,0.1

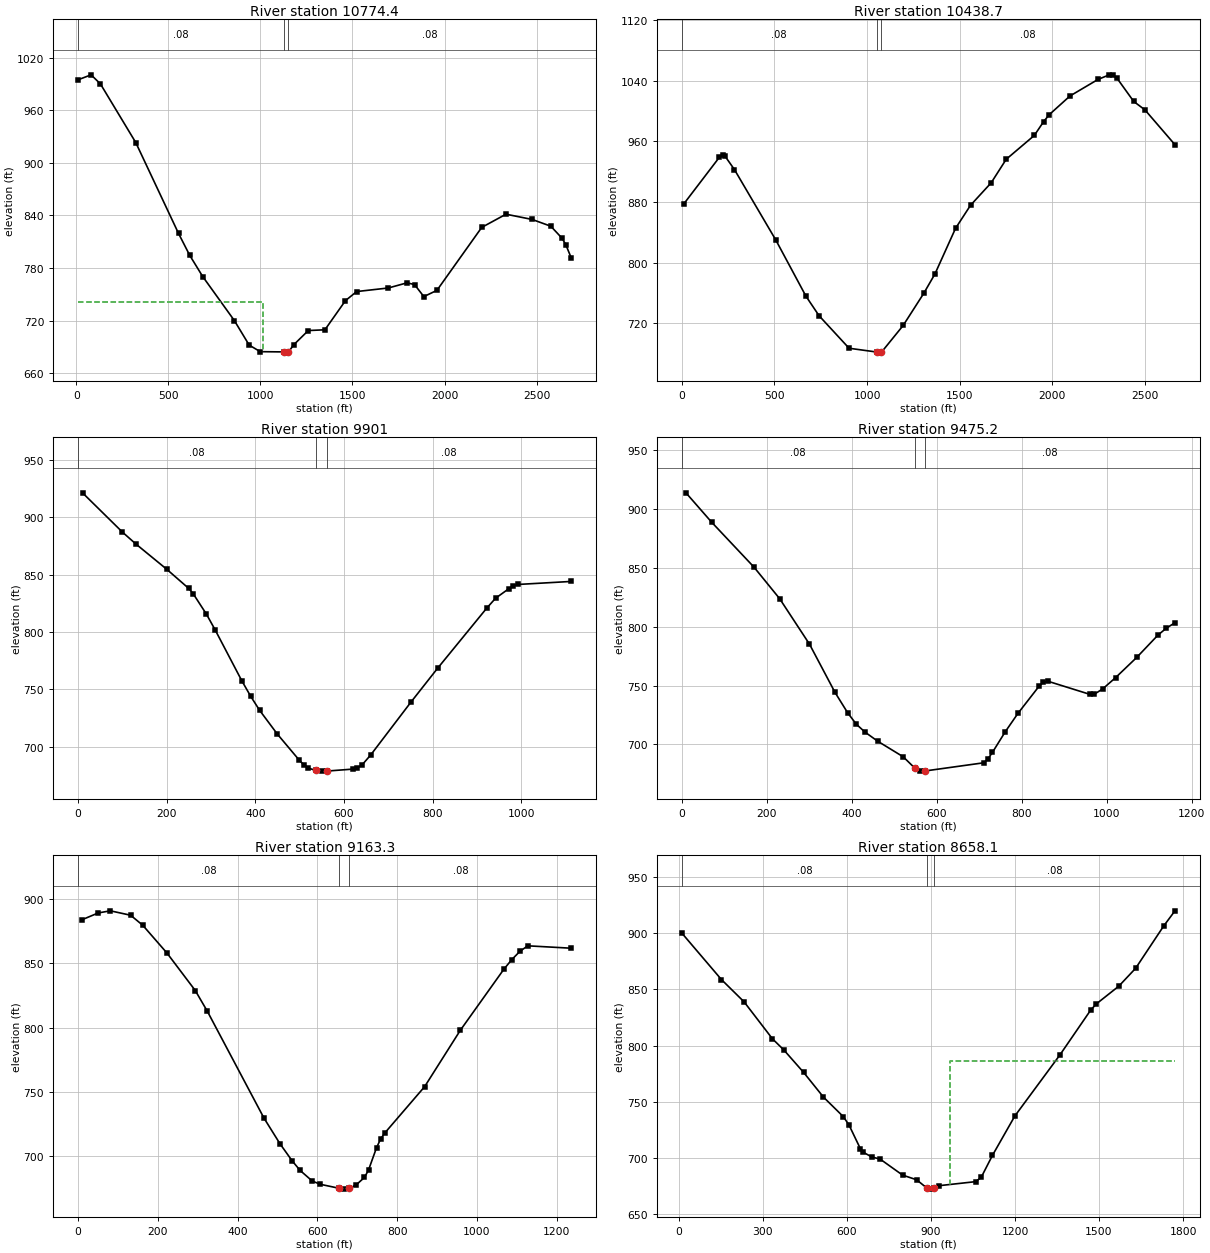
Type RM Length L Ch R = 1 ,10774.4 ,297.3,335.7,365.4
XS GIS Cut Line= 4
     1539367.946      388156.813     1540101.244      388641.639
     1540549.708      388496.191     1541622.384      387696.229
#Sta/Elev= 30
    10.1  994.81    80.8 1000.46   131.4   990.1   323.3  923.21   555.7  819.44
   616.4  794.48   687.1  770.25   858.9  720.02   939.3  692.07   999.5  684.58
  1127.4   684.3  1139.9  682.91  1152.4  683.99    1180  692.19  1260.3  708.68
  1350.5  709.53  1462.1  742.81  1522.9  753.17  1695.2  757.25  1796.6  763.13
  1837.1  761.14  1887.8  747.42  1958.8  754.52  2202.1  826.37  2333.9  841.43
  2475.8  835.45  2577.2  827.73    2638  814.07  2658.3   806.8  2688.7  791.32
#Mann= 3 , 0 , 0
    10.1     .08       0  1127.4    .045       0  1152.4     .08       0
#XS Ineff= 2 , 0
         1016.31  741.63
Permanent Ineff=
       F       F
Bank Sta=1127.4,1152.4
XS Rating Curve= 0 ,0
Exp/Cntr=0.3,0.1

Type RM Length L Ch R = 1 ,10438.7 ,532.8,537.7,543.1
XS GIS Cut Line= 4
     1539283.102       388659.82     1540095.184      388684.061
     1540573.949      388962.835     1541822.374      389308.273
#Sta/Elev= 30
    10.2  877.21   203.1  938.99   223.4  942.33   233.6  940.54   284.4  922.87
   507.8  829.92   670.3  755.92   741.4  730.04   903.1  687.24  1051.8  682.26
  1064.3   680.8  1076.8  681.68  1195.2  717.32    1306  759.57  1366.5  785.17
  1477.8  845.38  1558.7  875.79  1670.1  905.42    1751  936.37  1902.8  967.84
  1953.4  986.17  1983.8  995.33  2095.1 1019.82  2246.9 1041.73  2307.6 1047.74
  2327.8 1047.27  2348.1 1043.59  2439.2 1012.63  2499.9 1001.49  2661.8  955.57
#Mann= 3 , 0 , 0
       0     .08       0  1051.8    .045       0  1076.8     .08       0
Bank Sta=1051.8,1076.8
XS Rating Curve= 0 ,0
Exp/Cntr=0.3,0.1

Type RM Length L Ch R = 1 ,9901    ,411,425.8,440.5
XS GIS Cut Line= 3
     1539592.178      388835.569     1540024.266      389174.978
     1540464.864      389526.445
#Sta/Elev= 30
      10  921.15    99.9  887.02   129.9  876.78   199.8   854.7   249.8   837.9
   259.7  833.36   289.7  815.49   309.7  801.57   369.6  757.45   389.6  743.98
   409.6  731.86   449.6  711.16   499.5  688.26   509.5  684.33   519.5  681.54
     537  679.44   549.5  678.89     562  678.95   619.9  680.65     630  681.69
     640  683.93   660.2  692.89   750.7  738.74   811.1  768.33   921.8  820.59
     942  829.36   972.2  837.72   982.2  840.09   992.3  841.38  1113.1  844.02
#Mann= 3 , 0 , 0
       0     .08       0     537    .045       0     562     .08       0
Bank Sta=537,562
XS Rating Curve= 0 ,0
Exp/Cntr=0.3,0.1

Type RM Length L Ch R = 1 ,9475.2  ,298.4,311.9,325.2
XS GIS Cut Line= 3
      1539493.41      388889.558     1539725.505      389465.842
       1539906.1      389974.051
#Sta/Elev= 30
      10  913.71    70.1  888.89   170.3  850.51   230.5  823.79   300.6  785.22
   360.7  744.22   390.8  726.72   410.8  717.25   430.9  710.62   460.9  702.84
   521.1  689.57   548.6  679.89   561.1  677.38   573.6  677.57   711.2  684.49
   721.1  688.05   731.1  693.29   761.1  710.72   791.1   726.4     841  749.55
     851  752.87     861  753.78   960.9  742.52   970.8  742.66   990.8  747.29
  1020.8  756.75  1070.7  773.97  1120.7  792.95  1140.6  798.87  1160.6  803.38
#Mann= 3 , 0 , 0
       0     .08       0   548.6    .045       0   573.6     .08       0
Bank Sta=548.6,573.6
XS Rating Curve= 0 ,0
Exp/Cntr=0.3,0.1

Type RM Length L Ch R = 1 ,9163.3  ,512.2,505.1,498.1
XS GIS Cut Line= 4
     1539325.524       388865.87     1539489.153      389302.213
     1539458.851      389684.013       1539634.6      390029.451
#Sta/Elev= 30
    10.1  883.98    50.7  889.25      81  890.88   131.7  887.45   162.1  879.67
   222.9  858.01   293.8  828.86   324.2  812.63     466   729.6   506.3  709.54
   536.6  696.35   556.7  688.83     587  680.61   607.1  678.06   655.1  674.91
   667.6  674.29   680.1  674.83   697.8  677.76     718  683.41   728.1  689.12
   748.2   706.5   758.3   713.2   768.4  717.79   868.9  754.08   958.3  797.91
  1067.6  845.49  1087.5  852.98  1107.4  859.26  1127.3  863.65  1236.6  861.78
#Mann= 3 , 0 , 0
       0     .08       0   655.1    .045       0   680.1     .08       0
Bank Sta=655.1,680.1
XS Rating Curve= 0 ,0
Exp/Cntr=0.3,0.1

Type RM Length L Ch R = 1 ,8658.1  ,312.8,289.6,270.3
XS GIS Cut Line= 4
     1539301.283      388514.372     1538998.267      389132.524
     1539089.172       389635.53      1539451.05      390078.076
#Sta/Elev= 30
    10.1  899.99   151.9  858.61   232.9  838.78   334.1  805.97   374.6  796.12
   445.5   776.1   516.3  754.18   587.2  736.84   607.4  729.44   647.9  708.42
   658.1  705.28   688.4  701.08   718.5  699.17   798.7  684.95   848.8   680.8
   886.4  673.25   898.9   672.5   911.4  673.89     929  675.56  1059.3  679.14
  1079.3  682.91  1119.4  702.42  1199.6  737.48    1360  791.53  1470.4  831.54
  1490.4  836.97  1570.7  852.75  1630.8  868.64  1731.1  906.24  1771.2  919.64
#Mann= 3 , 0 , 0
    10.1     .08       0   886.4    .045       0   911.4     .08       0
#XS Ineff= 2 , 0
                          967.01          786.26
Permanent Ineff=
       F       F
Bank Sta=886.4,911.4
XS Rating Curve= 0 ,0
Exp/Cntr=0.3,0.1