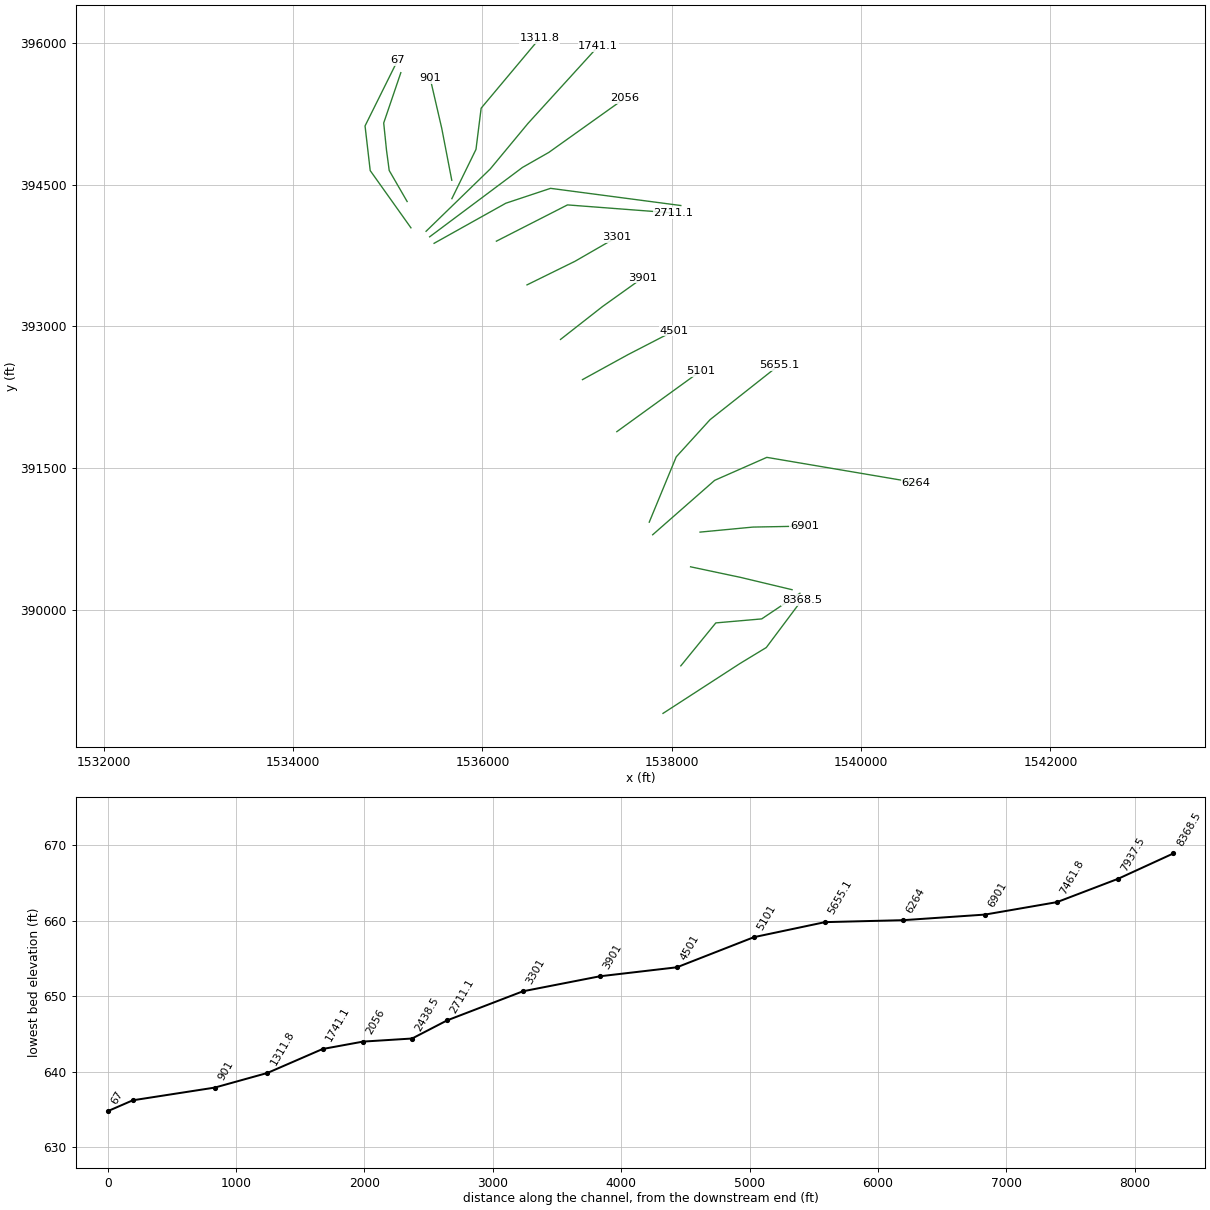
HEC-RAS study RFMILLCR.prj: RFMILLCR

--- RFMILLCR.g01 (geometry) --- (continued)

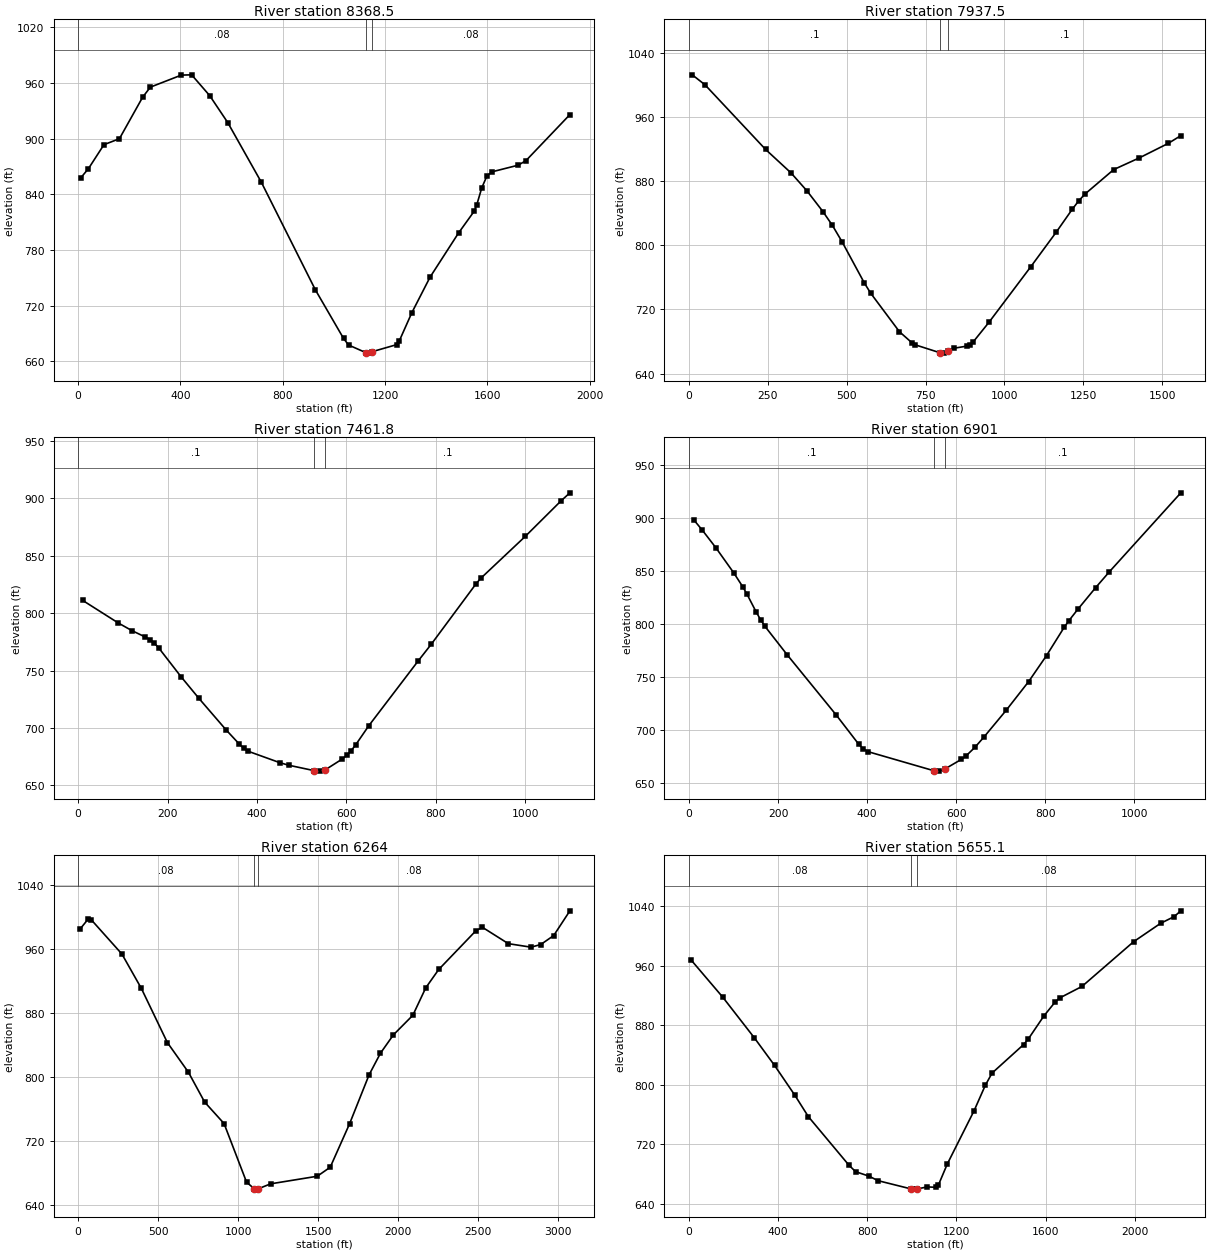
Type RM Length L Ch R = 1 ,8368.5  ,444.2,431,417.9
XS GIS Cut Line= 4
      1537907.41      388902.232     1538719.492       389429.48
     1538998.267      389599.168     1539374.007      390102.175
#Sta/Elev= 30
    10.1  857.63    40.3  867.61   100.9  893.42   161.4  899.84   252.1   944.5
   282.4  955.39   403.4  968.35   443.8  968.65   514.4  946.23     585  917.19
   716.1  853.04   927.9  736.84  1037.5   684.8  1057.2  677.66  1123.9  669.56
  1136.4  668.92  1148.9  670.43  1245.1  678.04    1255  681.77  1304.7  712.54
  1375.6  750.67    1487  798.26  1547.8  821.57  1557.9   828.2  1578.1  847.08
  1598.4  859.83  1618.6  864.24  1719.9  871.31  1750.3  876.12  1922.4  925.79
#Mann= 3 , 0 , 0
       0     .08       0  1123.9    .045       0  1148.9     .08       0
Bank Sta=1123.9,1148.9
XS Rating Curve= 0 ,0
Exp/Cntr=0.3,0.1

Type RM Length L Ch R = 1 ,7937.5  ,483.5,475.7,467.3
XS GIS Cut Line= 4
      1538095.28      389405.238     1538464.959      389859.762
     1538949.784      389902.184     1539353.622      390173.612
#Sta/Elev= 30
    10.1 1012.49    50.5 1000.05   242.4  919.56   323.2  890.24   373.8  867.82
   424.3  842.06   454.6  824.68   484.9  804.48   555.6  753.09   575.8  740.26
     667  692.24   707.5  678.15   717.7  675.82   796.4  665.93   808.9  665.56
   821.4  667.86   839.4  671.63   879.9  674.25   890.1  675.86   900.2  679.25
   950.9  704.05  1082.7  772.89  1163.8  816.23  1214.5  844.69  1234.7   855.1
    1255  863.79  1346.3  894.37  1427.4  908.93  1518.6   926.9  1559.1  936.68
#Mann= 3 , 0 , 0
       0      .1       0   796.4    .045       0   821.4      .1       0
Bank Sta=796.4,821.4
XS Rating Curve= 0 ,0
Exp/Cntr=0.3,0.1

Type RM Length L Ch R = 1 ,7461.8  ,552.4,560.9,567.7
XS GIS Cut Line= 3
     1538198.305      390453.673     1538727.099      390341.478
     1539270.981       390211.26
#Sta/Elev= 30
      10  811.12    90.1  791.35   120.1  784.81   150.2  779.21   160.2  777.01
   170.2  773.94   180.2  769.75   230.2  744.63   270.3  725.72   330.3  698.63
   360.4  686.02   370.4  682.31   380.4  679.75   450.5  669.91   470.5  667.65
   528.1  662.87   540.6  662.47   553.1  663.71   590.5  672.96   600.5  676.15
   610.5  680.24   620.5  685.22   650.4  702.16   760.3  758.29   790.2  773.14
   890.1  825.61   900.1  830.16    1000  866.79  1079.8  897.63  1099.8  904.71
#Mann= 3 , 0 , 0
       0      .1       0   528.1    .045       0   553.1      .1       0
Bank Sta=528.1,553.1
XS Rating Curve= 0 ,0
Exp/Cntr=0.3,0.1

Type RM Length L Ch R = 1 ,6901    ,628.2,636.9,647.8
XS GIS Cut Line= 3
     1538298.472      390820.863     1538857.588       390874.16
     1539400.733      390884.205
#Sta/Elev= 30
      10   898.8    30.1  888.58    60.2  872.13   100.3  848.41   120.4  835.37
   130.4  827.98   150.4  811.66   160.5  804.16   170.5  797.78   220.6  770.77
     331   713.7   381.1  686.31   391.1  681.94   401.2  679.33   549.2   661.3
   561.7  660.82   574.2  662.71     612  671.99     622  675.12   642.1  683.26
   662.3  692.94   712.6  718.42   762.8  745.44   803.1  770.11   843.3   797.2
   853.4  803.13   873.5  813.93   913.7  834.49   943.9  849.18  1104.9  924.07
#Mann= 3 , 0 , 0
       0      .1       0   549.2    .045       0   574.2      .1       0
Bank Sta=549.2,574.2
XS Rating Curve= 0 ,0
Exp/Cntr=0.3,0.1

Type RM Length L Ch R = 1 ,6264    ,599.1,609,618.8
XS GIS Cut Line= 4
     1537798.324      390793.051     1538452.839      391368.781
     1539003.959      391612.066      1540580.01       391344.54
#Sta/Elev= 30
    10.1  984.98    60.8  997.52    81.1  997.33   273.7  954.19   395.3  911.13
   557.5   843.5   689.2  806.31   790.6  768.99   911.9   742.1  1052.4  668.84
  1100.2  660.56  1112.7  660.08  1125.2  660.48    1203  666.71  1494.4  676.21
  1575.3  687.52  1696.7  742.12  1818.1  803.12    1889  830.12  1969.9  853.08
  2091.3  877.57  2172.2  911.97  2253.2  934.92  2485.9  983.46  2526.4  987.64
  2688.2  967.21  2829.9  962.81  2890.6  966.13  2971.5  977.33  3072.7 1008.29
#Mann= 3 , 0 , 0
       0     .08       0  1100.2    .045       0  1125.2     .08       0
Bank Sta=1100.2,1125.2
XS Rating Curve= 0 ,0
Exp/Cntr=0.3,0.1

Type RM Length L Ch R = 1 ,5655.1  ,558.5,554.1,549.6
XS GIS Cut Line= 4
     1537761.963      390926.378     1538046.797      391617.254
     1538404.356      392011.174     1539131.594      392586.904
#Sta/Elev= 30
    10.1  967.66   151.5  917.88   292.9  863.34   383.7  826.18   474.6  786.14
   535.2  757.35     717  692.17   747.3   683.3   807.5  677.27   847.7  671.22
   995.8  660.12  1008.3  659.82  1020.8  659.88  1068.5   662.8  1108.6  662.27
  1118.7  665.18  1158.8  693.62  1279.3  765.44  1329.7  799.67  1359.9  815.97
  1501.1  854.23  1521.3  861.32  1591.8  892.55  1642.2  911.29  1662.4  916.81
  1763.2  932.45  1995.1  992.65  2116.1 1017.35  2176.6 1026.32  2206.8 1034.14
#Mann= 3 , 0 , 0
       0     .08       0   995.8    .045       0  1020.8     .08       0
Bank Sta=995.8,1020.8
XS Rating Curve= 0 ,0
Exp/Cntr=0.3,0.1

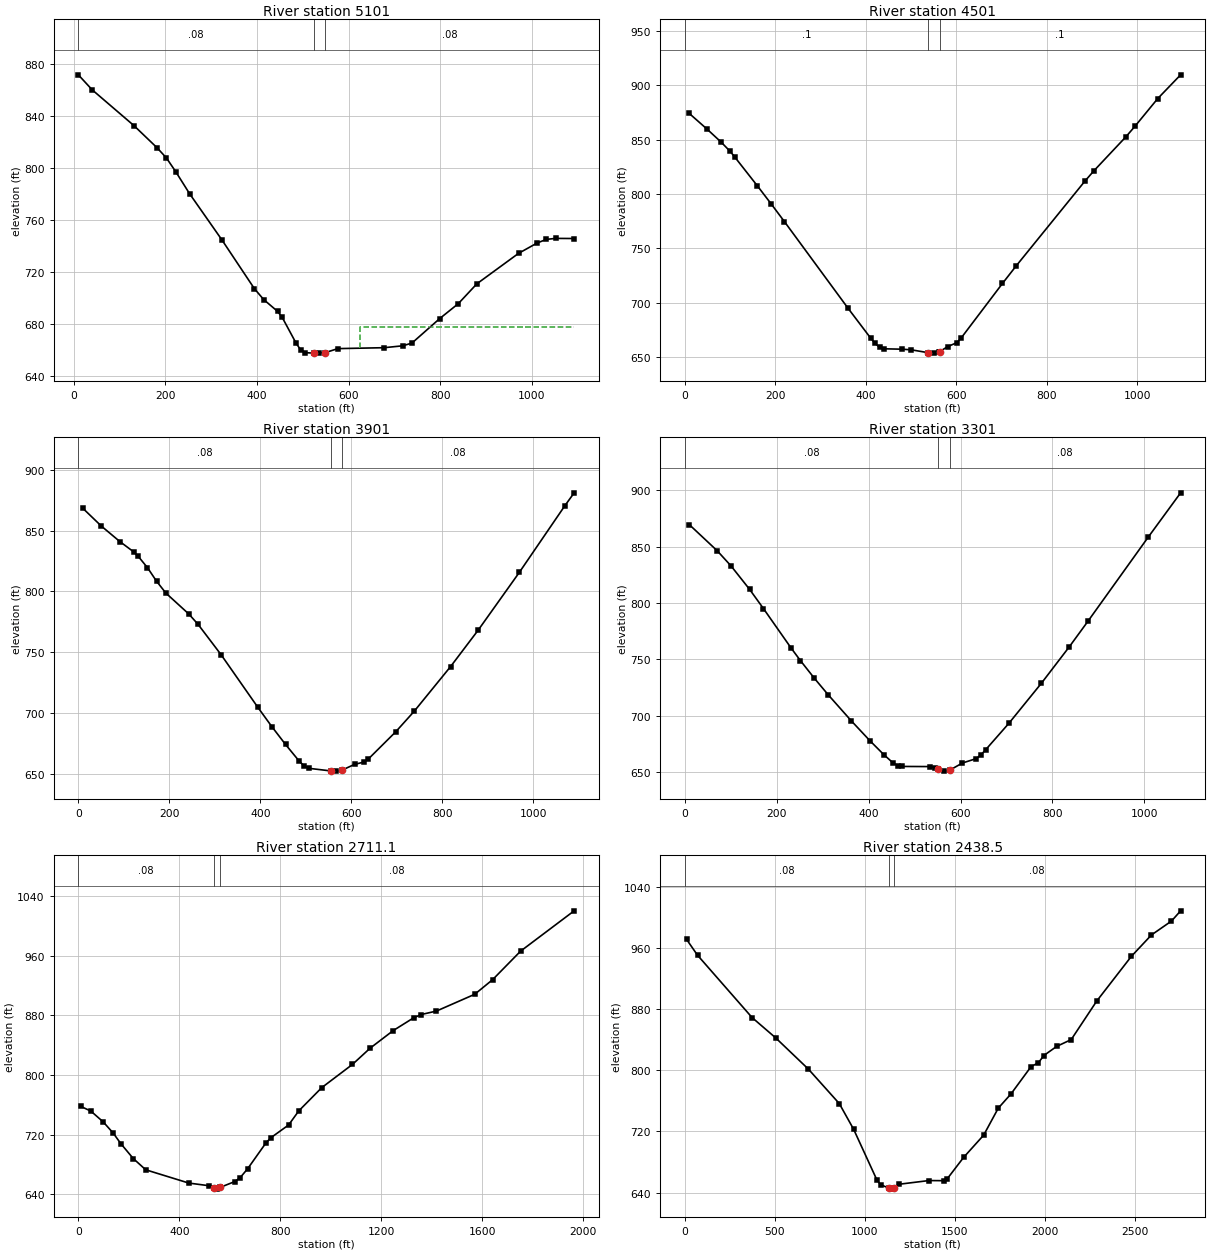
Type RM Length L Ch R = 1 ,5101    ,603.5,600,595.8
XS GIS Cut Line= 3
     1537419.482      391884.049     1537861.466      392204.621
      1538303.45      392525.192
#Sta/Elev= 30
    10.1  871.42    40.4  859.89   131.4  832.46     182  815.41   202.2  807.67
   222.4  797.22   252.8  780.21   323.6  744.63   394.3  707.28   414.6  698.93
   444.9  689.86     455  685.23   485.3  665.43   495.4  660.24   505.6  658.18
   523.4  657.84   535.9  657.83   548.4  658.16   576.3  661.29   677.4     662
   717.9  663.45   738.1  665.56   798.8   684.4   839.2   695.8   879.7  711.03
   970.7  734.41  1011.1  742.32  1031.3  745.13  1051.6  745.88    1092  745.79
#Mann= 3 , 0 , 0
    10.1     .08       0   523.4    .045       0   548.4     .08       0
#XS Ineff= 2 , 0
                          624.38          677.91
Permanent Ineff=
       F       F
Bank Sta=523.4,548.4
XS Rating Curve= 0 ,0
Exp/Cntr=0.3,0.1

Type RM Length L Ch R = 1 ,4501    ,596.7,600,602.7
XS GIS Cut Line= 3
     1537056.556       392434.83     1537539.248       392700.39
     1538023.564      392950.603
#Sta/Elev= 30
      10  873.96    50.1  859.26    80.1  847.75   100.2  839.19   110.2  834.11
   160.3  807.57   190.3  791.27   220.4  774.56   360.6  695.21   410.7  667.73
   420.7   662.7   430.7  659.15   440.7  657.82   480.8  657.44   500.8  656.88
   538.4  654.22   550.9  653.84     561  654.64   563.4  655.21   581.2  659.86
   601.4  663.43   611.5  668.05   702.3  717.88   732.6  733.99   884.1  811.63
   904.2  821.24   974.9  852.45   995.1  862.17  1045.6  887.72  1096.1  909.48
#Mann= 3 , 0 , 0
       0      .1       0   538.4    .045       0   563.4      .1       0
Bank Sta=538.4,563.4
XS Rating Curve= 0 ,0
Exp/Cntr=0.3,0.1

Type RM Length L Ch R = 1 ,3901    ,605.6,600,597.5
XS GIS Cut Line= 3
       1536824.4      392860.085     1537270.184      393209.901
     1537695.299      393514.133
#Sta/Elev= 30
    10.1  868.16    50.6  853.63    91.1  840.98   121.4  832.54   131.5  828.84
   151.8  819.58     172  808.35   192.3   798.7   242.9  781.46   263.1  773.02
   313.7  748.12   394.6  704.88     425  689.22   455.3   674.5   485.7  660.66
   495.8  657.03   505.9  654.98   554.2  652.84   566.7  652.65   579.2  653.45
   606.9  658.19     627  660.04     637  662.52   697.3  684.88   737.6  701.59
     818  738.45   878.3  768.17   968.8   815.6  1069.3   870.5  1089.4  880.91
#Mann= 3 , 0 , 0
       0     .08       0   554.2    .045       0   579.2     .08       0
Bank Sta=554.2,579.2
XS Rating Curve= 0 ,0
Exp/Cntr=0.3,0.1

Type RM Length L Ch R = 1 ,3301    ,589.5,589.9,588.4
XS GIS Cut Line= 3
     1536470.715      393437.689     1536976.488      393686.898
     1537422.585      393944.415
#Sta/Elev= 30
    10.1  869.56    70.5  846.46   100.7  832.93     141  812.15   171.2  795.05
   231.6  759.86   251.7   748.8   281.9  733.18   312.1  718.44   362.5  695.26
   402.7  677.72   432.9  665.37   453.1  657.97   463.2  655.64   473.2  654.82
   533.6   654.7   543.7  653.73   551.3  652.36   563.8  650.66   576.3  651.47
   604.2   657.9   634.5  661.81   644.6  665.21   654.7  669.67   705.2  693.14
   775.9  728.71   836.5  761.04   876.9  783.64  1008.2  858.45  1078.9  897.92
#Mann= 3 , 0 , 0
       0     .08       0   551.3    .045       0   576.3     .08       0
Bank Sta=551.3,576.3
XS Rating Curve= 0 ,0
Exp/Cntr=0.3,0.1

Type RM Length L Ch R = 1 ,2711.1  ,276.9,272.6,268.1
XS GIS Cut Line= 4
     1536147.365      393900.399     1536446.874      394053.501
     1536898.332      394284.265     1538016.496      394198.948
#Sta/Elev= 30
     9.9  757.84    49.5  751.66    98.9     737   138.5  721.94   168.2  707.98
   217.7  687.88   267.1  672.78   437.8  654.95   518.9  651.34   536.8  647.78
   549.3  646.81   561.8  649.12   620.3  657.02   640.6  661.98     671  674.21
     742  708.17   762.3  715.69   833.2  732.94   873.7  751.93   964.6   783.1
  1085.9  814.19  1156.6  836.18  1247.5  859.66  1328.3  876.77  1358.6  881.26
  1419.2  885.96  1570.8  908.48  1641.5  928.05  1752.6  966.42  1964.8 1020.55
#Mann= 3 , 0 , 0
       0     .08       0   536.8    .045       0   561.8     .08       0
Bank Sta=536.8,561.8
XS Rating Curve= 0 ,0
Exp/Cntr=0.3,0.1

Type RM Length L Ch R = 1 ,2438.5  ,366.5,382.5,398.6
XS GIS Cut Line= 4
     1535489.344      393877.752     1536246.883      394301.974
     1536719.588      394459.542      1538095.28      394277.733
#Sta/Elev= 30
    10.1  970.86    70.7  950.25   373.5   868.8   504.8  842.19   686.5  801.34
   858.1  756.29     938  722.59  1067.5  656.19  1087.5  650.31  1134.8  645.56
  1147.3  644.41  1159.8   645.4  1187.1   650.7  1356.5  655.63  1437.4  655.44
  1457.7   657.9  1548.8  685.91  1660.2  715.01  1741.3  750.29  1812.2  768.97
  1923.6  804.66  1964.1  809.58  1994.5  819.13  2065.4  830.99  2146.4  839.94
  2288.2  890.33  2480.7  948.81  2592.1  976.75  2703.5  994.94  2754.2  1008.3
#Mann= 3 , 0 , 0
       0     .08       0  1134.8    .045       0  1159.8     .08       0
Bank Sta=1134.8,1159.8
XS Rating Curve= 0 ,0
Exp/Cntr=0.3,0.1

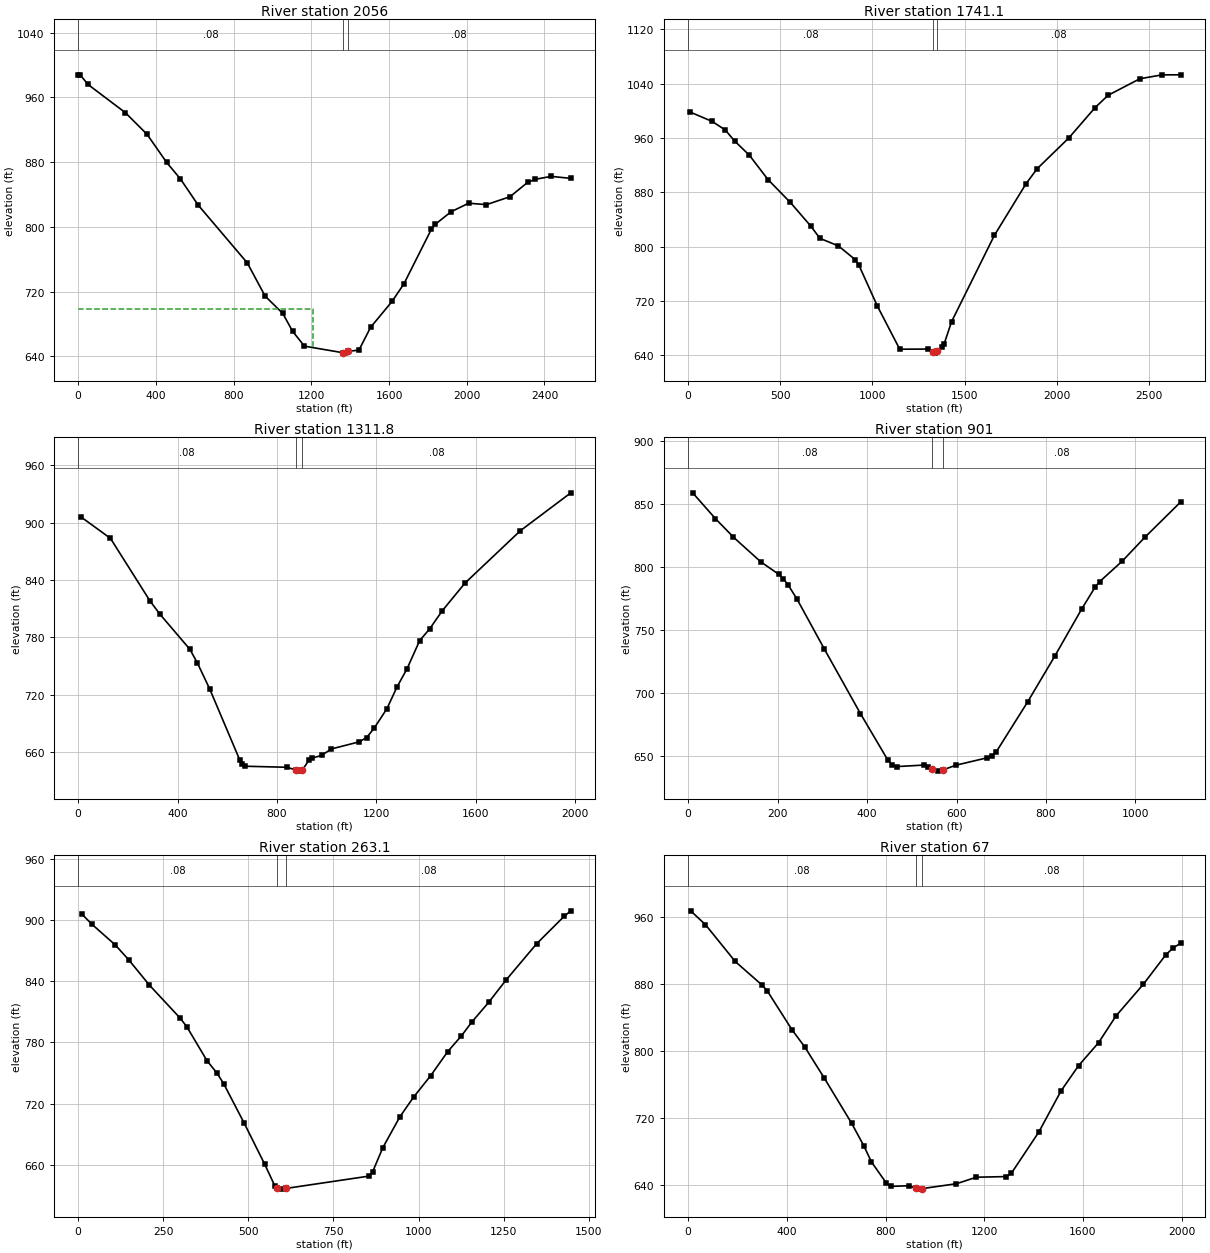
Type RM Length L Ch R = 1 ,2056    ,305.5,314.9,324.8
XS GIS Cut Line= 4
     1535442.413       393946.53     1536422.969      394680.954
     1536700.859      394839.749     1537506.741      395415.379
#Sta/Elev= 30
       0  987.92    10.1  987.92    50.6     976     243  941.13   354.4  914.42
   455.6   879.6   526.5   859.2   617.6  826.94   870.7  755.39   961.9  714.53
    1053  693.05  1103.6     671  1164.4  652.63  1362.6   644.5  1375.1     644
  1387.6  646.06  1445.1  647.76  1505.2  675.96  1615.9  708.01  1676.5  729.62
    1818  797.19  1838.2  803.26  1919.1   818.7    2010  829.28    2101  827.49
  2222.2  837.25  2313.2  854.99  2353.6  858.88  2434.5  862.43  2535.5  859.94
#Mann= 3 , 0 , 0
       0     .08       0  1362.6    .045       0  1387.6     .08       0
#XS Ineff= 2 , 0
         1210.09  698.49
Permanent Ineff=
       F       F
Bank Sta=1362.6,1387.6
XS Rating Curve= 0 ,0
Exp/Cntr=0.3,0.1

Type RM Length L Ch R = 1 ,1741.1  ,413.4,429.4,445.5
XS GIS Cut Line= 4
     1535404.499      394005.018     1536083.255      394665.593
     1536480.702      395146.369     1537222.594        395962.5
#Sta/Elev= 30
    10.1   998.1     131  984.13   201.5  971.62   251.9  955.52   332.5   934.4
   433.3  898.64   554.2  865.08     665  830.33   715.4  812.03   816.1  800.85
   906.8  780.66     927  772.44  1027.6  712.04  1148.4   648.8  1299.3  649.01
    1327  643.97  1339.5  643.02    1352  645.71  1379.8  651.61  1389.8  656.92
  1430.1  689.51    1662  816.35    1834  892.49  1894.7  914.67  2066.7  960.02
  2208.4 1004.47  2279.2 1022.67  2451.3 1047.02  2572.7 1052.83  2673.9 1052.84
#Mann= 3 , 0 , 0
       0     .08       0    1327    .045       0    1352     .08       0
Bank Sta=1327,1352
XS Rating Curve= 0 ,0
Exp/Cntr=0.3,0.1

Type RM Length L Ch R = 1 ,1311.8  ,401.5,410.8,421
XS GIS Cut Line= 4
     1535677.214      394350.456     1535931.747      394871.644
      1535986.29      395307.986     1536604.442      396047.345
#Sta/Elev= 30
      10  906.14     130  883.48     290  817.64     330  803.83     450  767.27
     480  753.03     530  725.62     650  651.84     660   647.1     670  644.99
   839.9  643.89   877.3  641.09   889.8  639.85   902.3  640.81   929.8  651.68
   939.8  653.23   979.8  656.34  1019.8  663.09  1131.3  670.48  1161.8  675.04
  1192.2     685  1242.9  705.12  1283.5  727.85  1324.1  747.01  1374.8   776.4
  1415.4  788.83  1466.1  807.75  1557.4  836.65  1780.6  891.53  1983.5  931.13
#Mann= 3 , 0 , 0
       0     .08       0   877.3    .045       0   902.3     .08       0
Bank Sta=877.3,902.3
XS Rating Curve= 0 ,0
Exp/Cntr=0.3,0.1

Type RM Length L Ch R = 1 ,901     ,639.5,637.8,634.5
XS GIS Cut Line= 3
     1535676.061      394544.996     1535570.582      395092.483
     1535448.276      395622.385
#Sta/Elev= 30
    10.1  858.67    60.8  838.28   101.4  823.46   162.2  803.99   202.7     794
   212.9  790.45     223  785.93   243.3  774.44   304.1  735.04   385.2  683.55
     446  646.95   456.2     643   466.3  641.51   527.1  642.72   537.3  641.41
   545.1  639.58   557.6  637.91   570.1   638.9   597.8  642.54   668.3  648.46
   678.4  649.72   688.5  653.02     759  692.81   819.4  728.94   879.8  766.46
     910  783.96   920.1  788.24   970.5  804.49  1020.8  823.29  1101.4  851.51
#Mann= 3 , 0 , 0
       0     .08       0   545.1    .045       0   570.1     .08       0
Bank Sta=545.1,570.1
XS Rating Curve= 0 ,0
Exp/Cntr=0.3,0.1

Type RM Length L Ch R = 1 ,263.1   ,196.6,196.2,196.5
XS GIS Cut Line= 5
     1535204.509      394320.155     1535015.289      394648.039
     1534986.338      394865.583      1534957.02      395151.141
     1535137.846      395683.726
#Sta/Elev= 30
      10  906.09    39.8  896.01   109.6  875.39   149.4  860.64   209.2  836.23
   298.9   804.1   318.8  795.61   378.6  762.08   408.5  749.67   428.4  739.03
   488.3  700.56   548.2  660.53   578.1  639.17   585.5  637.08     598  636.23
   610.5  636.91   855.4  649.03   865.3  653.34   895.1  676.84   945.3  707.15
   985.5  726.43  1035.7  747.42    1086  771.11  1126.1  786.45  1156.3  799.85
  1206.5  819.46  1256.7  840.97  1347.1  876.75  1427.4  903.45  1447.5     909
#Mann= 3 , 0 , 0
       0     .08       0   585.5    .045       0   610.5     .08       0
Bank Sta=585.5,610.5
XS Rating Curve= 0 ,0
Exp/Cntr=0.3,0.1

Type RM Length L Ch R = 1 ,67      ,57.4,67,76.5
XS GIS Cut Line= 4
     1535244.748      394041.531     1534814.466      394647.563
     1534759.923      395120.267     1535105.361      395817.204
#Sta/Elev= 30
      10  967.14    70.3  950.61   190.8  906.66   301.3  878.04   321.4  871.22
   421.8  824.73   472.1  804.87   552.4  767.13   662.9  713.37   713.1  685.93
   743.2  667.19     804  641.74   824.2  638.09   895.1  638.84   923.1     636
   935.6  634.78   948.1  635.38  1087.5  641.23  1168.5  649.03  1289.8  649.75
    1310  653.61  1421.1  702.78    1512  752.31  1582.8  782.33  1663.6  809.65
  1734.3  841.63  1845.4  879.52  1936.3  914.65  1966.6  923.01  1996.9  928.48
#Mann= 3 , 0 , 0
       0     .08       0   923.1    .045       0   948.1     .08       0
Bank Sta=923.1,948.1
XS Rating Curve= 0 ,0
Exp/Cntr=0.3,0.1
Stream Node=RFMILLCR        ,Main            , 0 , 0 ,Upstream end
Stream Node=RFMILLCR        ,Main            , 0 , 1 ,Downstream end

Chan Stop Cuts=-1
Use User Specified Reach Order=0